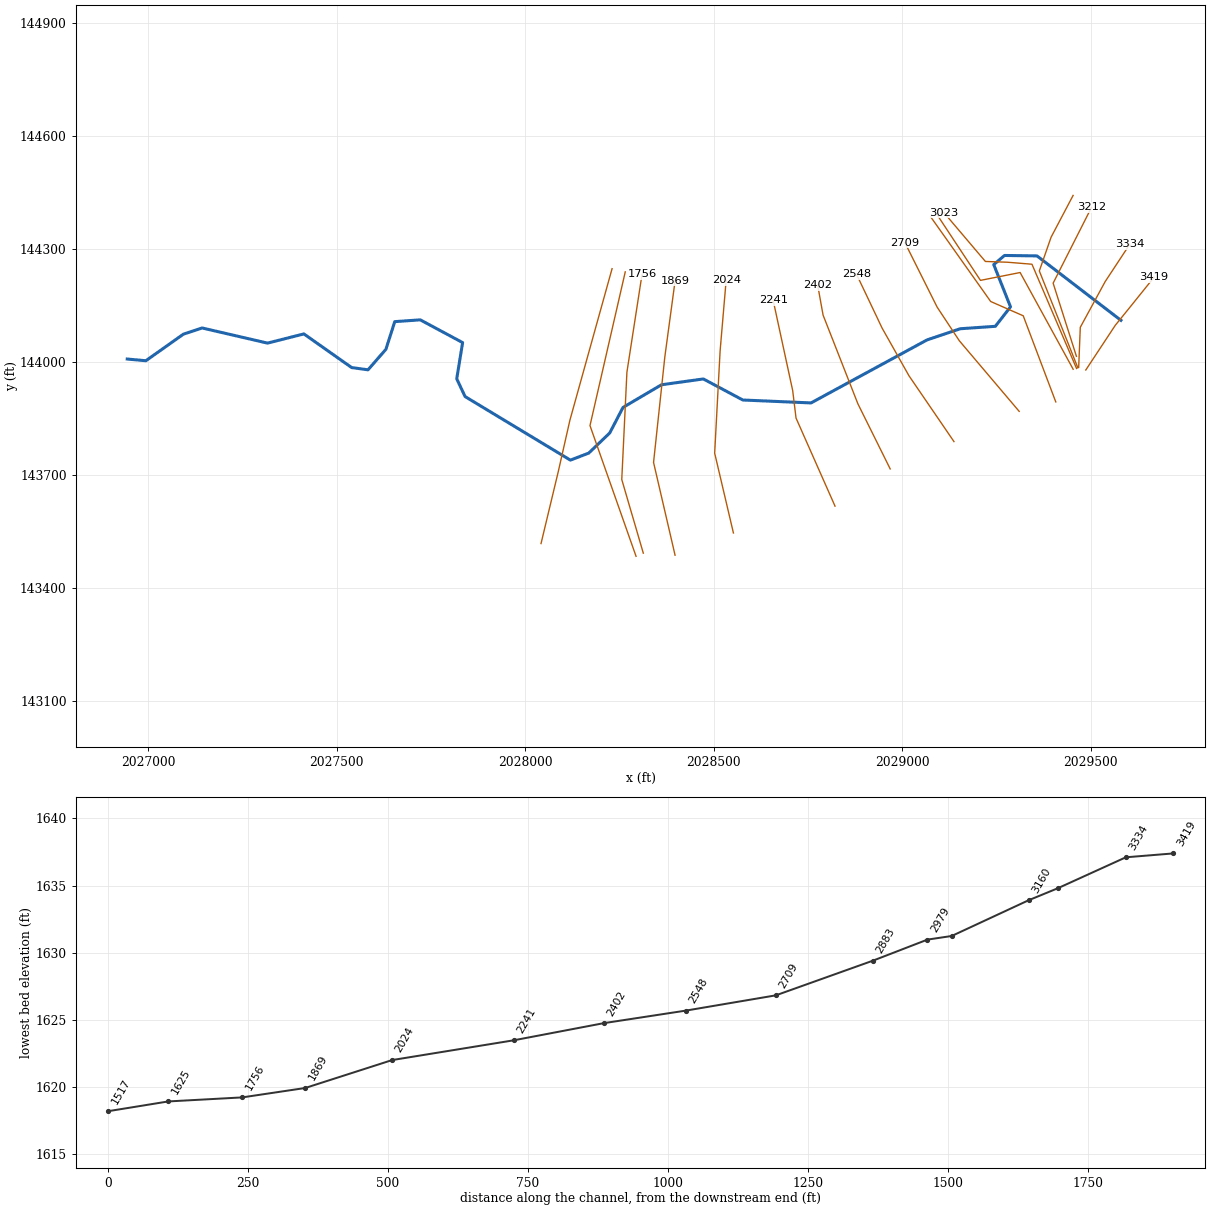
--- SCOTTBR.prj (project) ---

Proj Title=SCOTTBR
Current Plan=p01
Default Exp/Contr=0,0
English Units
Geom File=g01
Flow File=f01
Plan File=p01
Background Map Layer=Inundation Boundary (01pct Value_0)
Background Map Layer=Inundation Boundary (01pct Value_0)
BEGIN DESCRIPTION:
Stream Name: Scott Branch
Flood Zone: Detailed
Monroe County, West Virginia
HEC-RAS Version: 5.0.7
Vertical Datum: NAVD88
Projection: NAD 1983 StatePlane West Virginia S FIPS 4702 (US Feet)
LiDAR: 2016, 1-meter
Land Use: 2016 NLCD
Hydrology Method:
Regression.
Model Notes:
END DESCRIPTION:
DSS Export Rating Curves= 0
DSS Export Rating Curve Sorted= 0
DSS Export Volume Flow Curves= 0
DXF OffsetX= 0
DXF OffsetY= 0
DXF ScaleX= 0
DXF ScaleY= 0

--- SCOTTBR.p01 (plan) ---

Plan Title=Floodplain
Program Version=5.07
Short Identifier=Floodplain
Geom File=g01
Flow File=f01
Subcritical Flow
K Sum by GR= 0
Std Step Tol= 0.01
Critical Tol= 0.01
Num of Std Step Trials= 20
Max Error Tol= 0.3
Flow Tol Ratio= 0.001
Split Flow NTrial= 30
Split Flow Tol= 0.02
Split Flow Ratio= 0.02
Log Output Level= 0
Friction Slope Method= 1
Unsteady Friction Slope Method= 2
Unsteady Bridges Friction Slope Method= 1
Parabolic Critical Depth
Global Vel Dist= 0 , 0 , 0
Global Log Level= 0
CheckData=True
Encroach Param=-1 ,0,0, 2
Encroach River=ScottBr
Encroach Reach=Main
Encroach Node=3419
       1   150.3   177.3
Encroach Node=3334
       1     177     209
Encroach Node=3212
       1     216     256
Encroach Node=3160
       1     287   321.5
Encroach Node=3023
       1     381     411
Encroach Node=2979
       1  346.25   371.1
Encroach Node=2883
       1   277.3   301.9
Encroach Node=2709
       1   260.7   288.1
Encroach Node=2548
       1   256.3     280
Encroach Node=2402
       1   235.7   267.5
Encroach Node=2241
       1   285.4  318.36
Encroach Node=2024
       1     278     425
Encroach Node=1869
       1     438     478
Encroach Node=1756
       1     364     415
Encroach Node=1625
       1     284     336
Encroach Node=1517
       1   227.7   324.8
Encroach Node=1292
       1     260  384.86
Encroach Node=1020
       1     286   401.4
Encroach Node=895
       1     220     373
Encroach Node=616
       1   160.1     195
Encroach Node=403
       1   148.8  193.48
Encroach Node=232
       1     130     235
Encroach Node=73
       1    92.8     170
Mapping Interval=1HOUR
Computation Time Step Use Courant=        0
Computation Time Step Use Time Series=    0
Computation Time Step Count To Double=0
Computation Time Step Max Doubling=0
Computation Time Step Max Halving=0
Computation Time Step Residence Courant=0
Run HTab= 0
Run UNet= 0
Run Sediment= 0
Run PostProcess= 0
Run WQNet= 0
Run RASMapper=-1
UNET Theta= 0
UNET Theta Warmup= 0
UNET ZTol= 0
UNET ZSATol= 0
UNET MxIter= 0
UNET Max Iter WO Improvement= 0
UNET MaxInSteps= 0
UNET DtIC= 0
UNET DtMin= 0
UNET MaxCRTS= 0
UNET WFStab= 0
UNET SFStab= 0
UNET WFX= 1
UNET SFX= 1
UNET 1D Methodology=Finite Difference
UNET DSS MLevel= 1
UNET Pardiso=0
UNET DZMax Abort= 0
UNET Use Existing IB Tables= 0
UNET Froude Reduction=False
UNET Froude Limit= 0
UNET Froude Power= 0
UNET D1 Cores= 0
UNET D2 Coriolis=0
UNET D2 Cores= 0
UNET D2 Theta= 1
UNET D2 Theta Warmup= 1
UNET D2 Z Tol= 0.01
UNET D2 Volume Tol= 0.01
UNET D2 Max Iterations= 20
UNET D2 Equation= 0
UNET D2 RampUpFraction=0.1
UNET D2 TimeSlices= 1
UNET D2 BCVolumeCheck=0
UNET D1D2 MaxIter= 0
UNET D1D2 ZTol=0.01
UNET D1D2 QTol=0.1
UNET D1D2 MinQTol=1
Write IC File= 0
Write IC File at Fixed DateTime=0
Write IC File at Sim End=0
Echo Input=False
Echo Parameters=False
Echo Output=False
Write Detailed= 0
HDF Write Warmup=0
HDF Write Time Slices=0
HDF Flush=0
HDF Face Node Velocities=0
HDF Compression= 1
HDF Chunk Size= 1
HDF Spatial Parts= 1
HDF Use Max Rows=0
HDF Fixed Rows= 1
Calibration Method= 0
Calibration Iterations= 20
Calibration Max Change=0.05
Calibration Tolerance=0.2
Calibration Maximum=1.5
Calibration Minimum=0.5
Calibration Optimization Method= 1
WQ AD Non Conservative
WQ ULTIMATE=-1
WQ Max Comp Step=1HOUR
WQ Output Interval=15MIN
WQ Output Selected Increments= 0
WQ Output face flow=0
WQ Output face velocity=0
WQ Output face area=0
WQ Output face dispersion=0
WQ Output cell volume=0
WQ Output cell surface area=0
WQ Output cell continuity=0
WQ Output cumulative cell continuity=0
WQ Output face conc=0
WQ Output face dconc_dx=0
WQ Output face courant=0
WQ Output face peclet=0
WQ Output face adv mass=0
WQ Output face disp mass=0
WQ Output cell mass=0
WQ Output cell source sink temp=0
WQ Output nsm pathways=0
WQ Output nsm derived pathways=0
WQ Output MaxMinRange=-1
WQ Daily Max Min Mean=-1
WQ Daily Range=0
WQ Daily Time=0
WQ Create Restart=0
WQ Fixed Restart=0
WQ System Summary=0
WQ Write To DSS=0
WQ Use Fixed Temperature=0
Sorting and Armoring Iterations= 10
XS Update Threshold= 0.02
Bed Roughness Predictor= 0
Hydraulics Update Threshold= 0.02
Energy Slope Method= 1
Volume Change Method= 1
Sediment Retention Method= 0
XS Weighting Method= 0
Number of US Weighted Cross Sections= 1
Number of DS Weighted Cross Sections= 1
Upstream XS Weight=0
Main XS Weight=1
Downstream XS Weight=0
Number of DS XS's Weighted with US Boundary= 1
Upstream Boundary Weight= 1
Weight of XSs Associated with US Boundary= 0
Number of US XS's Weighted with DS Boundary= 1
Downstream Boundary Weight= 0.5
Weight of XSs Associated with DS Boundary= 0.5
Percentile Method= 0
Sediment Output Level= 3
Mass or Volume Output= 0
Output Increment Type= 1
Profile and TS Output Increment= 1
XS Output Flag= 0
XS Output Increment= 10
Write Gradation File= 0
Read Gradation Hotstart= 0
Write HDF5 File= 1
Write Binary Output= 1
Write DSS Sediment File= 0
SV Curve= 0
Specific Gage Flag= 0

--- SCOTTBR.f01 (steady flow) ---

Flow Title=Flow
Program Version=5.07
Number of Profiles= 7
Profile Names=01pct,FW,10pct,04pct,02pct,0_2pct,01plus
River Rch & RM=ScottBr,Main            ,3419
    1040    1040     563     741     886    1440    1540
River Rch & RM=ScottBr,Main            ,1517
    1370    1370     748     979    1170    1880    2020
Boundary for River Rch & Prof#=ScottBr,Main            , 1
Up Type= 0
Dn Type= 3
Dn Slope=0.02023
Boundary for River Rch & Prof#=ScottBr,Main            , 2
Up Type= 0
Dn Type= 3
Dn Slope=0.02023
Boundary for River Rch & Prof#=ScottBr,Main            , 3
Up Type= 0
Dn Type= 3
Dn Slope=0.02023
Boundary for River Rch & Prof#=ScottBr,Main            , 4
Up Type= 0
Dn Type= 3
Dn Slope=0.02023
Boundary for River Rch & Prof#=ScottBr,Main            , 5
Up Type= 0
Dn Type= 3
Dn Slope=0.02023
Boundary for River Rch & Prof#=ScottBr,Main            , 6
Up Type= 0
Dn Type= 3
Dn Slope=0.02023
Boundary for River Rch & Prof#=ScottBr,Main            , 7
Up Type= 0
Dn Type= 3
Dn Slope=0.02023
DSS Import GetInterval= 0
DSS Import GetPeak= 0
DSS Import FillOption= 0

--- SCOTTBR.g01 (geometry) ---

Geom Title=Geometry
Program Version=5.07

River Reach=ScottBr         ,Main
Reach XY= 30
     2029580.441      144110.701     2029357.778      144281.625
     2029271.718      144282.772     2029243.091      144258.656
     2029287.588      144146.4262029247.39790623144094.850288129
     2029154.293      144088.399      2029066.29      144058.826
      2028758.47      143891.641     2028577.535      143899.391
     2028472.841      143955.258     2028361.754      143939.772
     2028259.767       143879.67     2028224.525      143811.897
     2028168.776      143758.498     2028120.222      143739.922
     2027840.898      143908.519     2027818.737      143955.626
     2027834.353      144051.668      2027722.02      144111.989
     2027654.357      144107.255     2027630.869      144033.847
     2027583.465      143979.476     2027540.056      143985.418
     2027413.361      144074.651     2027316.873      144050.281
     2027143.519      144090.431     2027093.818      144074.057
      2026994.21      144003.5482026944.84128876144008.029747309

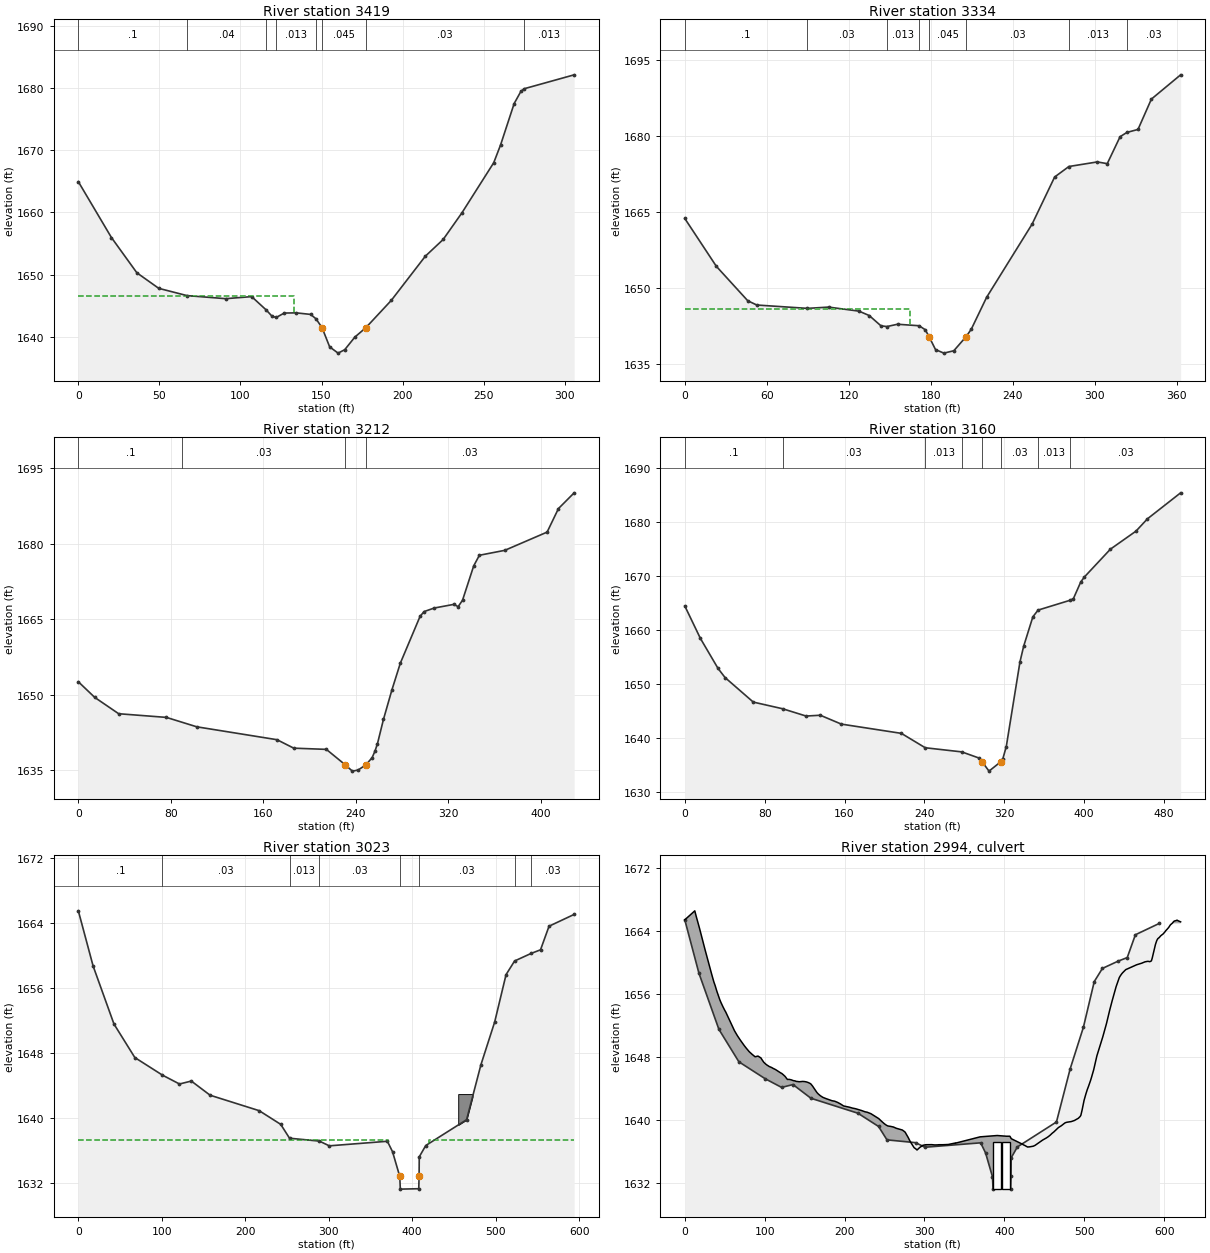
Type RM Length L Ch R = 1 ,3419    ,81.6,85,87.5
XS GIS Cut Line= 4
     2029487.272      143978.979     2029565.545      144097.616
     2029598.542      144138.287     2029668.374      144225.001
#Sta/Elev= 30
       0 1664.95    20.4 1655.98    36.1 1650.31    49.6 1647.81   67.021646.644
    90.9 1646.15   106.9 1646.48  115.921644.325   119.6 1643.29  122.171643.147
     127 1643.84   134.4 1643.87   143.3 1643.62  146.581642.914   150.3  1641.5
     155 1638.41   160.2  1637.4   164.3 1637.95   170.6 1639.99   177.3 1641.48
     193 1645.87     214 1652.97     225 1655.66   236.6 1659.95   256.2    1668
   260.4 1670.84   268.8 1677.51     273 1679.48  275.05 1679.89   305.8 1682.12
#Mann= 8 ,-1 , 0
       0      .1       0   67.02     .04       0  115.92     .03       0
  122.17    .013       0  146.58     .03       0   150.3    .045       0
   177.3     .03       0  275.05    .013       0
#XS Ineff= 2 , 0
          132.88 1646.56
Permanent Ineff=
       F       F
Bank Sta=150.3,177.3
XS Rating Curve= 0 ,0
Exp/Cntr=0.3,0.1

Type RM Length L Ch R = 1 ,3334    ,121,121.7,122.6
XS GIS Cut Line= 4
     2029468.394      143986.038     2029472.692      144092.244
     2029538.686       144213.49     2029603.914      144312.482
#Sta/Elev= 30
       0 1663.73    23.1 1654.27    46.1 1647.46    52.7 1646.62   89.781645.957
   105.2 1646.21   127.5 1645.41     135 1644.54   143.6  1642.5  147.961642.367
   155.7 1642.82  171.551642.522     176 1641.73  178.76 1640.38   183.5 1637.81
   189.6 1637.11   196.9 1637.58   205.9 1640.37   209.7 1641.85   220.9 1648.14
   254.2 1662.62   270.7 1671.93  281.131674.005   301.9 1674.91   309.2 1674.57
   318.6  1679.9  323.621680.747   331.7 1681.33   341.5 1687.33   362.9 1692.13
#Mann= 8 ,-1 , 0
       0      .1       0   89.78     .03       0  147.96    .013       0
  171.55     .03       0  178.76    .045       0   205.9     .03       0
  281.13    .013       0  323.62     .03       0
#XS Ineff= 2 , 0
          165.04 1645.76
Permanent Ineff=
       F       F
Bank Sta=178.76,205.9
XS Rating Curve= 0 ,0
Exp/Cntr=0.3,0.1

Type RM Length L Ch R = 1 ,3212    ,49.2,51.9,53.5
XS GIS Cut Line= 3
2029462.41253364144015.2729328842029400.62994021144209.322486909
2029502.44069277144410.333459912
#Sta/Elev= 30
       0 1652.55    14.2 1649.44    34.9  1646.2    76.2 1645.47   102.5  1643.6
   171.9 1641.04   186.4 1639.36   214.6 1639.12   230.8 1636.08   237.1  1634.8
     242 1635.01   248.91636.057   254.2 1637.48   256.7 1638.79   258.8 1640.24
     264 1645.07   271.3 1650.92   278.6 1656.24   295.7 1665.55   299.2 1666.49
   307.9 1667.19     325 1667.92   328.6 1667.46   332.4 1668.73   342.1 1675.57
     347 1677.67     369 1678.65   405.6 1682.27   415.4 1686.94     429 1690.07
#Mann= 4 ,-1 , 0
       0      .1       0      90     .03       0   230.8    .045       0
   248.9     .03       0
Bank Sta=230.8,248.9
XS Rating Curve= 0 ,0
Exp/Cntr(USF)=0,0
Exp/Cntr=0.3,0.1

Type RM Length L Ch R = 1 ,3160    ,99.4,137.2,164.6
XS GIS Cut Line= 4
     2029466.167      143984.801     2029364.025       144241.67
     2029395.241       144331.29     2029453.644      144442.055
#Sta/Elev= 30
       0 1664.44    15.6 1658.45    33.3 1652.89    40.3 1651.21    68.6 1646.67
   97.871645.444   121.5 1644.09   135.7 1644.24   156.8  1642.6   216.9 1640.89
  240.82 1638.23  277.431637.465   294.2 1636.36   297.7 1635.66   304.7 1633.91
   316.5 1635.65   318.6 1636.23     322 1638.46   335.7 1654.11   339.4    1657
   348.6 1662.43  353.861663.676  386.011665.497   389.2 1665.79   396.6 1668.88
   400.3 1669.81   426.3 1674.94   451.9 1678.27   463.4 1680.55   496.6 1685.35
#Mann= 8 ,-1 , 0
       0      .1       0   97.87     .03       0  240.82    .013       0
  277.43     .03       0   297.7    .045       0   316.5     .03       0
  353.86    .013       0  386.01     .03       0
Bank Sta=297.7,316.5
XS Rating Curve= 0 ,0
Exp/Cntr=0.5,0.3

Type RM Length L Ch R = 1 ,3023    ,40.2,43.3,45
BEGIN DESCRIPTION:
Merged DS Survey SCB032CU
END DESCRIPTION:
XS GIS Cut Line= 5
     2029462.758      143983.037     2029344.491      144259.538
      2029279.24      144264.839     2029220.922      144266.878
     2029111.219      144396.157
#Sta/Elev= 30
       0 1665.45    17.7 1658.67    42.7 1651.54    67.7 1647.42  100.831645.257
   121.2 1644.17   135.4 1644.53   157.9 1642.79   216.7 1640.89   242.5 1639.21
  253.051637.506  288.821637.151   300.7 1636.57   370.3 1637.13   376.5 1635.84
  385.14 1632.81   385.8 1631.25   407.9  1631.3   408.3 1632.86   408.5 1635.22
   416.3 1636.61   465.2 1639.78   482.4 1646.54   498.9  1651.8   512.5 1657.61
  522.731659.286   542.51660.214   553.8 1660.66     564 1663.56   594.1 1665.01
#Mann= 8 ,-1 , 0
       0      .1       0  100.83     .03       0  253.05    .013       0
  288.82     .03       0  385.14    .045       0   408.3     .03       0
  522.73    .013       0   542.5     .03       0
#XS Ineff= 2 , 0
             371  1637.3     420          1637.3
Permanent Ineff=
       F       F
#Block Obstruct= 1 ,-1
455.1715472.3833 1642.93
Bank Sta=385.14,408.3
XS Rating Curve= 0 ,0
Exp/Cntr=0.5,0.3

Type RM Length L Ch R = 2 ,2994    ,,,
BEGIN DESCRIPTION:
Williams RD
Merged Survey data SCB030RP
Culvert Opening: Span 10 and Rise 6
Deck information taken from LiDAR
END DESCRIPTION:
Bridge Culvert--1,0,-1,-1, 0
Deck Dist Width WeirC Skew NumUp NumDn MinLoCord MaxHiCord MaxSubmerge Is_Ogee
11.8,22,2.6,0, 200, 198, , , 0.98, 0, 0,0,,
     .02   12.51   14.29   18.43   20.87   21.66   25.34   32.71   33.75    36.4
   37.94   40.08   42.81   43.77   45.25   47.69   50.13   51.14   62.19   65.88
   69.77   74.51   76.97   80.62   84.18   87.99   91.58   95.36   96.45   98.89
  101.33  102.73  105.79  108.64   110.1  113.52  118.39   120.2  121.16  123.27
  125.71   127.4  128.53  130.58  133.02   135.9   137.9  139.58  140.34  143.27
  147.65  150.09  152.53  154.96   157.4  158.01  159.84  161.69  165.38  167.15
  169.59  172.75  176.43  184.22  187.49   189.1  191.17  194.86  198.54  199.44
  205.91   209.6  213.85  221.05  225.67  228.26  231.71  232.98  242.73  246.45
  250.05  252.48  253.82  254.92  257.51  261.19  264.67  268.56  269.55  272.25
  274.43  275.93  276.87  279.62  281.74   283.3  285.89  286.99  289.06  290.67
  293.93  298.04  301.73   309.1  312.78  316.47  318.06   323.1  329.67  338.81
  338.91  369.61  386.51  386.96  387.86  387.96     391  402.61   406.9  408.55
  408.65  409.55     422   422.1  423.58  425.53  429.04  431.55  436.09  438.44
  447.86  452.57  454.93  457.28  459.64  461.99  467.66  471.41  475.69  476.74
  478.47  483.71  487.72   492.6  494.96  495.75  497.31  499.76  502.02  503.77
  505.23  507.78  509.08  511.44   511.8  515.81   518.5  520.86  523.21  527.84
  530.28  531.86  534.99  537.34  539.88  542.05  543.89  545.13  546.76   547.9
  551.92  563.95   565.6  571.98  575.99  579.72  582.08  584.01  584.43  585.03
  586.79  588.03  589.14  590.73  592.04  593.85  596.05  598.56  600.92  602.13
  603.27  605.63  607.83  610.34   612.1  613.53  615.04  616.11   617.4  620.62
 1665.46  1666.6  1665.9 1664.38 1663.42  1663.1 1661.67 1658.89 1658.51 1657.56
 1657.12  1656.4 1655.61 1655.32 1654.96 1654.43 1653.94 1653.77 1651.37 1650.73
 1650.14 1649.47 1649.15 1648.71 1648.38 1648.06 1648.15 1647.91 1647.72 1647.36
 1647.13 1647.02 1646.82  1646.7 1646.61 1646.44 1646.11    1646 1645.96 1645.78
 1645.55 1645.31 1645.18 1645.19 1645.14 1645.03    1645 1644.93 1644.93 1644.89
 1644.93 1644.91 1644.86 1644.77 1644.64 1644.58 1644.35 1644.08 1643.52 1643.33
 1643.12 1642.91 1642.76 1642.48 1642.42 1642.35 1642.27 1642.07 1641.83  1641.8
 1641.66 1641.55 1641.46 1641.24 1641.07 1641.02 1640.89 1640.83 1640.21 1639.85
 1639.53 1639.36 1639.29 1639.26 1639.22 1639.14 1638.98 1638.87 1638.83 1638.76
  1638.6 1638.47 1638.29 1637.81 1637.38 1637.11 1636.71 1636.52 1636.37 1636.22
 1636.53 1636.82 1636.89  1636.9 1636.86 1636.87 1636.89 1636.89 1636.92 1637.11
 1637.09 1637.89 1638.03 1638.03 1638.04 1638.04 1638.06 1637.97 1637.97 1637.67
 1637.66 1637.61 1636.99 1637.01 1636.89  1636.8  1636.6 1636.62  1636.7 1636.81
 1637.48 1637.75 1637.91  1638.1 1638.33 1638.52 1639.07 1639.31 1639.65  1639.7
 1639.75 1639.83 1639.97 1640.25 1640.49 1640.63  1641.3 1642.52 1643.33 1643.89
 1644.28 1645.02 1645.45 1646.28 1646.41 1648.18 1649.07 1649.82  1650.6 1652.29
 1653.33 1653.99  1655.2 1656.04 1656.97 1657.62 1658.13 1658.34 1658.58 1658.72
 1659.13 1659.68 1659.75 1659.95 1660.12 1660.19 1660.14 1660.24 1660.37 1660.58
 1661.31 1661.87 1662.34 1662.82 1663.06 1663.21 1663.46 1663.65 1663.92 1664.09
 1664.21 1664.48 1664.82 1665.04 1665.26 1665.33 1665.36 1665.42 1665.34  1665.2
                                                                                
                                                                                
                                                                                
                                                                                
                                                                                
                                                                                
                                                                                
                                                                                
                                                                                
                                                                                
                                                                                
                                                                                
                                                                                
                                                                                
                                                                                
                                                                                
                                                                                
                                                                                
                                                                                
                                                                                
   -26.9  -25.12  -20.98  -18.54  -17.75  -14.07    -6.7   -5.66   -3.01   -1.47
     .67     3.4    4.36    5.84    8.28   10.72   11.73   22.78   26.47   30.36
    35.1   37.56   41.21   44.77   48.58   52.17   55.95   57.04   59.48   61.92
   63.32   66.38   69.23   70.69   74.11   78.98   80.79   81.75   83.86    86.3
   87.99   89.12   91.17   93.61   96.49   98.49  100.17  100.93  103.86  108.24
  110.68  113.12  115.55  117.99   118.6  120.43  122.28  125.97  127.74  130.18
  133.34  137.02  144.81  148.08  149.69  151.76  155.45  159.13  160.03   166.5
  170.19  174.44  181.64  186.26  188.85   192.3  193.57  203.32  207.04  210.64
  213.07  214.41  215.51   218.1  221.78  225.26  229.15  230.14  232.84  235.02
  236.52  237.46  240.21  242.33  243.89  246.48  247.58  249.65  251.26  254.52
  258.63  262.32  269.69  273.37  277.06  278.65  283.69  290.26   299.4   299.5
   330.2   347.1  349.01  349.91  350.01  351.59   363.2   370.5  372.64  382.59
  382.69  384.17  386.12  389.63  392.14  396.68  399.03  408.45  413.16  415.52
  417.87  420.23  422.58  428.25     432  436.28  437.33  439.06   444.3  448.31
  453.19  455.55  456.34   457.9  460.35  462.61  464.36  465.82  468.37  469.67
  472.03  472.39   476.4  479.09  481.45   483.8  488.43  490.87  492.45  495.58
  497.93  500.47  502.64  504.48  505.72  507.35  508.49  512.51  524.54  526.19
  532.57  536.58  540.31  542.67   544.6  545.02  545.62  547.38  548.62  549.73
  551.32  552.63  554.44  556.64  559.15  561.51  562.72  563.86  566.22  568.42
  570.93  572.69  574.12  575.63   576.7  577.99  581.21   603.5
  1666.6  1665.9 1664.38 1663.42  1663.1 1661.67 1658.89 1658.51 1657.56 1657.12
  1656.4 1655.61 1655.32 1654.96 1654.43 1653.94 1653.77 1651.37 1650.73 1650.14
 1649.47 1649.15 1648.71 1648.38 1648.06 1648.15 1647.91 1647.72 1647.36 1647.13
 1647.02 1646.82  1646.7 1646.61 1646.44 1646.11    1646 1645.96 1645.78 1645.55
 1645.31 1645.18 1645.19 1645.14 1645.03    1645 1644.93 1644.93 1644.89 1644.93
 1644.91 1644.86 1644.77 1644.64 1644.58 1644.35 1644.08 1643.52 1643.33 1643.12
 1642.91 1642.76 1642.48 1642.42 1642.35 1642.27 1642.07 1641.83  1641.8 1641.66
 1641.55 1641.46 1641.24 1641.07 1641.02 1640.89 1640.83 1640.21 1639.85 1639.53
 1639.36 1639.29 1639.26 1639.22 1639.14 1638.98 1638.87 1638.83 1638.76  1638.6
 1638.47 1638.29 1637.81 1637.38 1637.11 1636.71 1636.52 1636.37 1636.22 1636.53
 1636.82 1636.89  1636.9 1636.86 1636.87 1636.89 1636.89 1636.92 1637.11 1637.09
 1637.89 1638.03 1638.04 1638.05 1638.05 1638.06 1637.97 1637.97 1637.54 1636.99
 1637.01 1636.89  1636.8  1636.6 1636.62  1636.7 1636.81 1637.48 1637.75 1637.91
  1638.1 1638.33 1638.52 1639.07 1639.31 1639.65  1639.7 1639.75 1639.83 1639.97
 1640.25 1640.49 1640.63  1641.3 1642.52 1643.33 1643.89 1644.28 1645.02 1645.45
 1646.28 1646.41 1648.18 1649.07 1649.82  1650.6 1652.29 1653.33 1653.99  1655.2
 1656.04 1656.97 1657.62 1658.13 1658.34 1658.58 1658.72 1659.13 1659.68 1659.75
 1659.95 1660.12 1660.19 1660.14 1660.24 1660.37 1660.58 1661.31 1661.87 1662.34
 1662.82 1663.06 1663.21 1663.46 1663.65 1663.92 1664.09 1664.21 1664.48 1664.82
 1665.04 1665.26 1665.33 1665.36 1665.42 1665.34  1665.2 1664.96
                                                                                
                                                                                
                                                                                
                                                                                
                                                                                
                                                                                
                                                                                
                                                                                
                                                                                
                                                                                
                                                                                
                                                                                
                                                                                
                                                                                
                                                                                
                                                                                
                                                                                
                                                                                
                                                                                
                                                                
BR Coef=-1 ,-1 , 0 ,, 0 ,,,0.8,0,1.2,0,
WSPro=,,,, 1 ,,,, 0 ,,,, 0 ,,,,-1 ,-1 ,-1 , 0 , 0 , 0 , 0 , 0
Multiple Barrel Culv=2,6,10,23,0.013,0.4,1,8,1,1631.26,1631.04, 2,Culvert #1  , 0 ,14
   390.9  354.75   401.9  365.75
BC Culvert Barrel=1,Barrel #1,0
BC Culvert Barrel=2,Barrel #2,0
Culvert Bottom n=0.013
BC Design=,, 0 ,, 0 ,,,,,,
BC HTab HWMax=0
BC HTab TWMax=0
BC HTab MaxFlow=0
BC Use User HTab Curves=0
BC User HTab FreeFlow(D)= 0

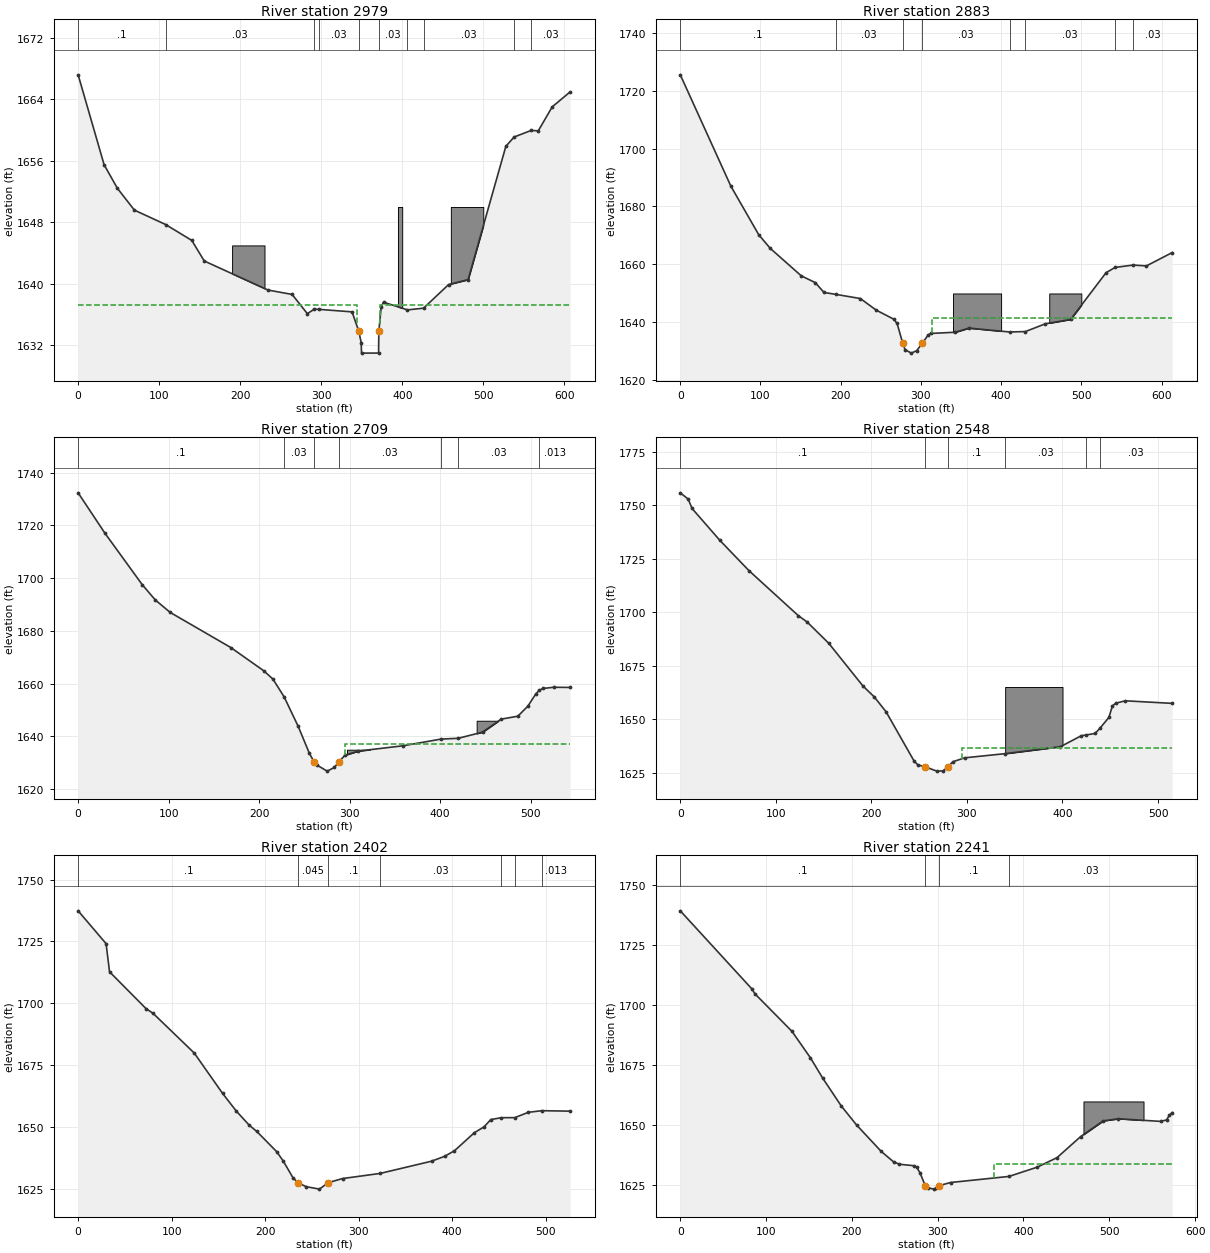
Type RM Length L Ch R = 1 ,2979    ,101.6,96.8,81.6
BEGIN DESCRIPTION:
Merged US Survey SCB028CD
END DESCRIPTION:
XS GIS Cut Line= 4
     2029453.786      143980.998     2029313.089      144237.516
     2029207.872      144216.717     2029093.683      144389.632
#Sta/Elev= 30
       0  1667.2   32.05  1655.5   48.45 1652.43   69.45 1649.59  108.061647.713
  140.25 1645.65  155.65 1642.97  234.25 1639.19  264.05 1638.62  282.85 1636.12
  291.491636.702  297.721636.672  338.05 1636.35  346.25 1633.85  349.32 1632.36
  349.73 1630.98  370.77 1630.99   371.1 1633.86  374.05 1637.04  376.85 1637.61
  406.461636.608  426.241636.829  457.25 1639.91  481.25 1640.55  527.85  1657.9
  538.09 1659.11  559.111659.962  567.85 1659.91  585.05 1663.03  607.05 1664.97
#Mann= 10 ,-1 , 0
       0      .1       0  108.06     .03       0  291.49    .013       0
  297.72     .03       0  346.25    .045       0   371.1     .03       0
  406.46    .013       0  426.24     .03       0  538.09    .013       0
  559.11     .03       0
#XS Ineff= 2 , 0
             344  1637.3     372          1637.3
Permanent Ineff=
       F       F
#Block Obstruct= 3 ,-1
     190     230    1645 394.661399.9256    1650459.9584499.9803    1650
Bank Sta=346.25,371.1
XS Rating Curve= 0 ,0
Exp/Cntr=0.5,0.3

Type RM Length L Ch R = 1 ,2883    ,177.6,173.8,159.9
XS GIS Cut Line= 4
     2029407.644      143894.324     2029321.327      144122.748
      2029235.01      144160.644      2029076.06      144384.858
#Sta/Elev= 30
       0 1725.42    63.1 1686.99    97.8 1670.26   112.2 1665.55   150.8 1656.09
   168.3 1653.74   179.2 1650.34  193.941649.691   224.5 1648.25   244.2 1644.27
     266 1641.15   270.3 1639.66   277.3 1632.88   280.2 1630.65     288 1629.42
   294.7 1630.26   301.9 1632.86     309 1635.69   312.5 1636.21   342.9 1636.63
   359.9 1638.06  410.631636.715  430.271636.858   455.2 1639.54   486.6 1641.04
   530.8 1657.15  542.011658.978  564.461659.793   581.2 1659.51   613.3 1664.11
#Mann= 8 ,-1 , 0
       0      .1       0  193.94     .03       0   277.3    .045       0
   301.9     .03       0  410.63    .013       0  430.27     .03       0
  542.01    .013       0  564.46     .03       0
#XS Ineff= 2 , 0
                           313.9         1641.46
Permanent Ineff=
       F       F
#Block Obstruct= 2 ,-1
     340     400    1650     460     500    1650
Bank Sta=277.3,301.9
XS Rating Curve= 0 ,0
Exp/Cntr=0.3,0.1

Type RM Length L Ch R = 1 ,2709    ,161.8,161.1,159.8
XS GIS Cut Line= 4
     2029310.574      143869.254     2029151.916      144056.434
     2029093.088      144145.568      2029007.52      144316.704
#Sta/Elev= 30
       0 1732.33    29.5 1717.08    70.9 1697.47    85.3  1691.7   101.7    1687
   168.7 1673.68   204.9 1664.92   215.2 1661.74  227.711654.913   243.2 1643.75
   255.5 1633.58   260.7 1630.32   264.4    1629   275.2 1626.83   283.1 1628.21
   288.1 1630.38   294.9 1632.86   309.4 1634.42   359.4 1636.46  400.81 1638.97
  420.041639.281   446.8 1641.61   467.4 1646.53   485.8 1647.65   496.8 1651.41
   505.4 1655.95  509.311657.434   513.4 1658.16   525.7 1658.63   543.5 1658.55
#Mann= 7 ,-1 , 0
       0      .1       0  227.71     .03       0   260.7    .045       0
   288.1     .03       0  400.81    .013       0  420.04     .03       0
  509.31    .013       0
#XS Ineff= 2 , 0
                          294.84         1637.22
Permanent Ineff=
       F       F
#Block Obstruct= 2 ,-1
297.0266323.1615 1634.96440.3175464.2524 1645.94
Bank Sta=260.7,288.1
XS Rating Curve= 0 ,0
Exp/Cntr=0.3,0.1

Type RM Length L Ch R = 1 ,2548    ,149.2,145.8,143.1
Node Name=B
XS GIS Cut Line= 4
     2029137.655      143789.034     2029018.216      143963.735
     2028946.909      144090.305     2028879.168      144232.918
#Sta/Elev= 30
       0 1755.73     8.3 1752.79    12.3 1748.43    41.3 1733.57    71.9 1719.36
   123.6 1698.31   132.7 1695.39   155.4 1685.42   191.1 1665.51   203.1 1660.33
   215.4 1653.39   244.8 1630.31   248.7 1628.61   256.3 1627.72   268.4 1625.69
   275.1  1625.8     280  1627.7   285.2 1630.06   297.6  1631.9  340.191633.865
   397.8  1637.1   419.6 1642.21   424.71642.594   434.1 1643.28  439.211645.746
   448.5 1650.75   452.3 1656.19   455.8 1657.44   465.8 1658.55   514.8 1657.35
#Mann= 6 ,-1 , 0
       0      .1       0   256.3    .045       0     280      .1       0
  340.19     .03       0   424.7    .013       0  439.21     .03       0
#XS Ineff= 2 , 0
                          294.84         1636.69
Permanent Ineff=
       F       F
#Block Obstruct= 1 ,-1
     340400.0112    1665
Bank Sta=256.3,280
XS Rating Curve= 0 ,0
Exp/Cntr=0.3,0.1

Type RM Length L Ch R = 1 ,2402    ,162.8,161.2,150.7
XS GIS Cut Line= 4
     2028968.474      143716.578     2028882.703       143889.42
     2028790.434      144124.641     2028776.138      144203.915
#Sta/Elev= 30
       0 1737.39    29.9  1724.1    33.6 1712.71    72.8 1697.75    80.1 1695.93
   124.2 1679.84   154.5 1663.52   169.1 1656.39   182.9 1650.68   191.1 1648.11
   212.3 1639.96   219.4 1636.13   229.9 1629.32   235.7 1627.22     244 1625.76
   258.1 1624.76   267.5 1627.37   282.8 1629.04  323.021631.114     378 1636.06
   392.1 1638.05   402.6  1640.3   423.8 1647.58   434.3 1649.98   441.4 1652.91
  452.73 1653.67  467.071653.688   481.6 1655.85  495.951656.499   526.2 1656.32
#Mann= 7 ,-1 , 0
       0      .1       0   235.7    .045       0   267.5      .1       0
  323.02     .03       0  452.73    .013       0  467.07     .03       0
  495.95    .013       0
Bank Sta=235.7,267.5
XS Rating Curve= 0 ,0
Exp/Cntr=0.3,0.1

Type RM Length L Ch R = 1 ,2241    ,207.7,216.7,201.6
XS GIS Cut Line= 4
     2028822.122      143617.897     2028718.727      143851.427
     2028709.814      143924.516     2028658.117      144163.394
#Sta/Elev= 30
       0  1739.4    83.4 1706.89      87 1704.84   130.1 1689.23   151.6 1678.22
     166  1669.7   187.5 1658.18   205.4 1650.21   234.1 1639.22   248.5 1634.86
   255.4 1633.84   272.2 1633.24   275.5 1632.56   279.4 1630.28   285.4 1624.98
   288.7 1624.09   295.2 1623.48   298.6 1623.84   301.9 1624.97   315.1 1626.24
  383.051628.773     416 1632.63   439.1  1636.6   466.5 1645.34   492.8  1651.9
   510.6  1652.8     560 1651.69   566.7 1652.31     570 1654.24   573.3 1655.38
#Mann= 4 ,-1 , 0
       0      .1       0   285.4    .045       0   301.9      .1       0
  383.05     .03       0
#XS Ineff= 2 , 0
                          365.33         1634.04
Permanent Ineff=
       F       F
#Block Obstruct= 1 ,-1
469.8903 539.874    1660
Bank Sta=285.4,301.9
XS Rating Curve= 0 ,0
Exp/Cntr=0.3,0.1

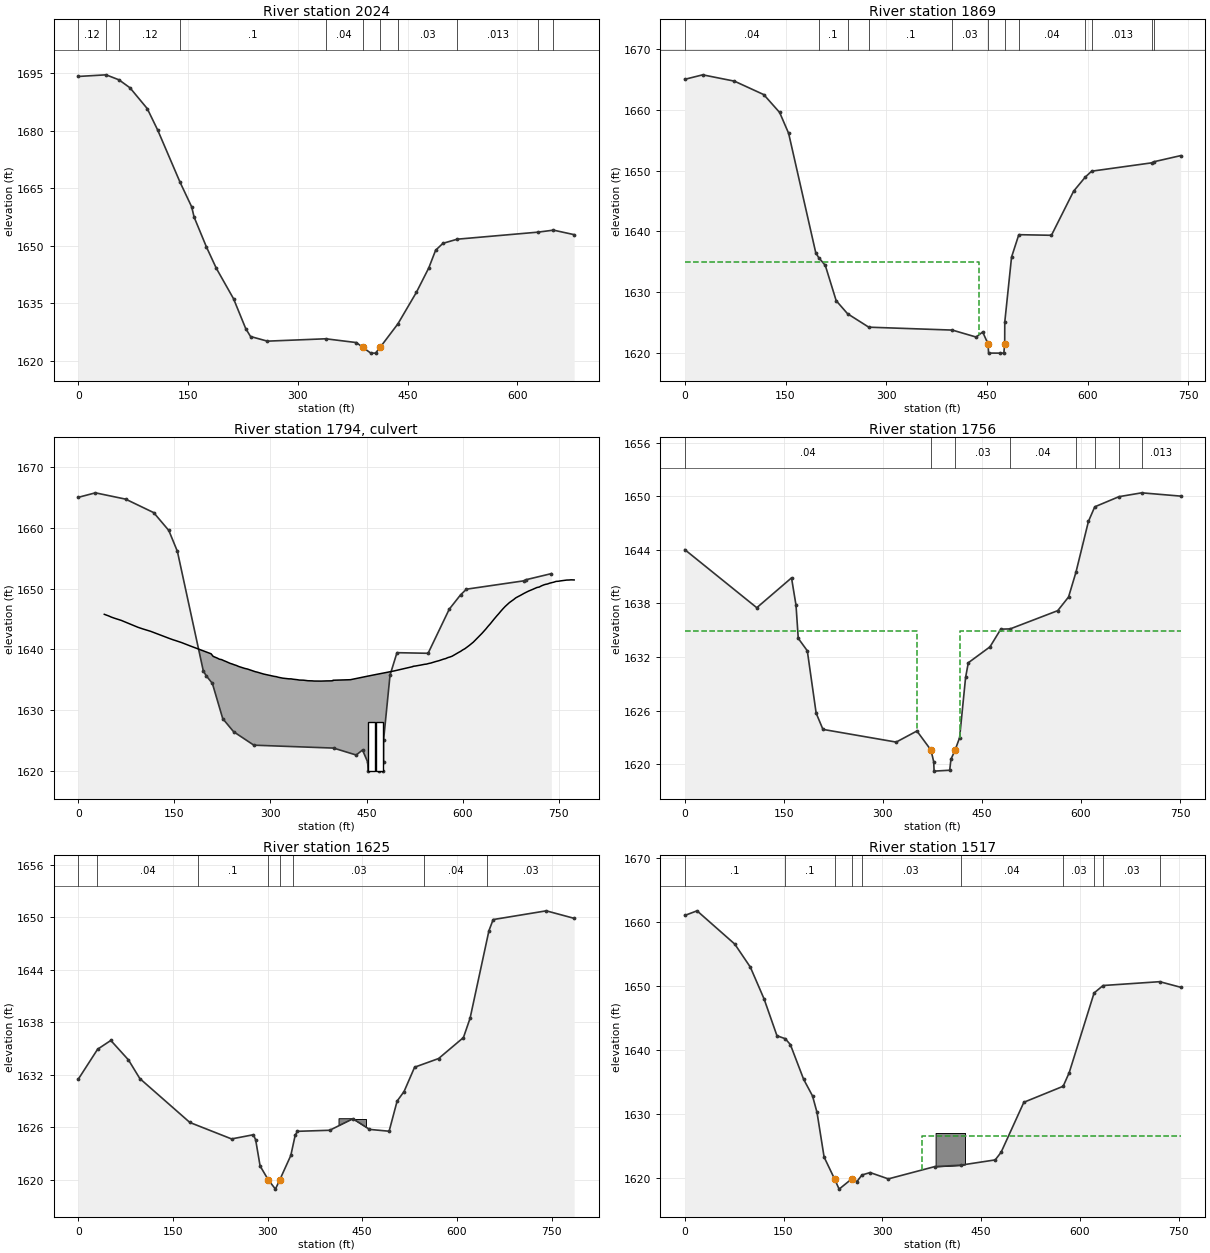
Type RM Length L Ch R = 1 ,2024    ,158.3,155.2,153
XS GIS Cut Line= 4
     2028552.619      143546.704     2028502.883      143758.485
     2028517.322      144029.629     2028533.367      144217.344
#Sta/Elev= 30
       0 1694.08   37.921694.503   55.491693.202    70.6 1691.12    94.2  1685.7
   108.5 1680.09  139.021666.513   154.9  1660.1   158.2 1657.44   175.1 1649.64
   188.6 1644.09   212.1 1636.17   228.7 1628.41   235.3 1626.34   258.3 1625.13
  338.121625.747   379.9 1624.76   388.4 1623.56   399.6 1622.01   406.1 1622.01
   412.7  1623.6  436.681629.641     462 1637.87   478.9 1644.23   488.2 1648.81
   498.2 1650.61  517.791651.689  628.171653.526  649.271654.045   677.5 1652.87
#Mann= 11 ,-1 , 0
       0     .12       0   37.92      .1       0   55.49     .12       0
  139.02      .1       0  338.12     .04       0   388.4    .045       0
   412.7     .04       0  436.68     .03       0  517.79    .013       0
  628.17     .03       0  649.27    .013       0
Bank Sta=388.4,412.7
XS Rating Curve= 0 ,0
Exp/Cntr=0.5,0.3

Type RM Length L Ch R = 1 ,1869    ,100.9,112.4,117.1
BEGIN DESCRIPTION:
Merged DS Survey SCB022CU
END DESCRIPTION:
XS GIS Cut Line= 4
     2028397.847      143487.762     2028340.801      143733.771
     2028370.738       144014.15     2028398.023      144216.227
#Sta/Elev= 30
       0 1665.03   26.65 1665.77   73.85 1664.73  117.65 1662.51  141.25 1659.57
  154.65 1656.13  195.05 1636.46  199.431635.661  209.25 1634.38  225.45 1628.57
  242.441626.416  274.021624.204  398.481623.725  433.85 1622.58  443.65 1623.41
   451.7 1621.43  452.41 1619.94  470.05 1619.93  475.15 1619.94  476.45 1621.43
  476.53 1625.02  486.65 1635.75  497.46 1639.44  546.05 1639.34  579.05  1646.6
  596.661648.954  605.961649.899  695.981651.282  698.531651.449  738.45 1652.46
#Mann= 12 ,-1 , 0
       0     .04       0  199.43      .1       0  242.44     .04       0
  274.02      .1       0  398.48     .03       0   451.7    .045       0
  476.45     .03       0  497.46     .04       0  596.66     .03       0
  605.96    .013       0  695.98    .013       0  698.53     .03       0
#XS Ineff= 2 , 0
             438 1634.99     488            1636
Permanent Ineff=
       F       F
Bank Sta=451.7,476.45
XS Rating Curve= 0 ,0
Exp/Cntr=0.5,0.3

Type RM Length L Ch R = 2 ,1794    ,,,
BEGIN DESCRIPTION:
State Line Rd
Merged  Survey data SCB020RP
Culvert Opening: Span 11.5 and Rise 8
Deck information taken from LiDAR
END DESCRIPTION:
Bridge Culvert--1,0,-1,-1, 0
Deck Dist Width WeirC Skew NumUp NumDn MinLoCord MaxHiCord MaxSubmerge Is_Ogee
30,34,2.6,0, 114, 114, , , 0.98, 0, 0,0,,
   40.54   47.66   51.49   56.86   66.99   93.13  100.75  112.84  142.71  148.02
   152.5  161.28  174.41  207.25  210.53   217.1  220.38  223.66  227.54  230.67
   236.8  240.14  243.36  246.65  250.29  259.78  263.98   276.2  279.48  289.33
  305.75  309.03  312.32  318.89  328.74  332.02   335.3  341.87  345.15  351.72
  358.29  364.86  368.14  378.97  387.19  394.75  397.57  397.67  424.79  452.43
  453.33  453.43  453.89   462.3  475.48  475.58  476.48  493.33  522.35  522.45
  524.19  526.07  533.61  540.28   543.6  546.93  550.26  557.31  562.99  570.24
  573.57  576.89  580.22  583.55  594.33  596.83  600.15  603.46  610.08   616.7
  629.95  632.19  636.57  639.88   643.2  648.52  653.13  656.44  659.75  663.06
  666.38     673  679.62  682.93  686.25  690.43  696.18   702.8  709.43  716.05
  719.56  722.67  726.78  729.29  732.61  735.92  742.54  745.85  749.16  752.48
  762.41  766.15  769.06  774.09
 1645.76 1645.48  1645.3  1645.1 1644.76 1643.62 1643.35 1642.96 1641.76 1641.56
 1641.41  1641.1 1640.56 1639.26 1638.83 1638.54 1638.36  1638.3 1638.11 1637.98
 1637.69 1637.58 1637.45 1637.34 1637.17 1636.85 1636.75 1636.31 1636.23 1635.92
 1635.54 1635.49 1635.39 1635.25 1635.13 1635.13 1635.07 1634.99 1634.93 1634.91
 1634.82  1634.8 1634.77 1634.76 1634.79  1634.8 1634.83  1634.9 1634.99 1635.59
 1635.61 1635.61 1635.62  1635.8 1636.07 1636.07 1636.09 1636.44 1637.15 1637.19
 1637.22 1637.24 1637.38 1637.52 1637.56 1637.66 1637.73 1637.96 1638.12 1638.38
 1638.47 1638.63 1638.73 1638.86 1639.52 1639.66  1639.9 1640.09 1640.61 1641.18
  1642.6 1642.86 1643.38 1643.81  1644.2  1644.9 1645.48 1645.87 1646.29 1646.68
 1647.05 1647.69 1648.19 1648.47 1648.66 1648.89 1649.23 1649.58 1649.87 1650.18
 1650.25 1650.43 1650.61 1650.69 1650.76 1650.89 1651.06 1651.18  1651.2 1651.26
  1651.4 1651.41 1651.44 1651.42
                                                                                
                                                                                
                                                                                
                                                                                
                                                                                
                                                                                
                                                                                
                                                                                
                                                                                
                                                                                
                                                                                
                                
  -21.06  -13.94  -10.11   -4.74    5.39   31.53   39.15   51.24   81.11   86.42
    90.9   99.68  112.81  145.65  148.93   155.5  158.78  162.06  165.94  169.07
   175.2  178.54  181.76  185.05  188.69  198.18  202.38   214.6  217.88  227.73
  244.15  247.43  250.72  257.29  267.14  270.42   273.7  280.27  283.55  290.12
  296.69  303.26  306.54  317.37  325.59  333.15  335.97  336.07  363.19  376.12
  377.02  377.12  392.29   400.2   400.3   400.7   401.2  431.73  460.75  460.85
  462.59  464.47  472.01  478.68     482  485.33  488.66  495.71  501.39  508.64
  511.97  515.29  518.62  521.95  532.73  535.23  538.55  541.86  548.48   555.1
  568.35  570.59  574.97  578.28   581.6  586.92  591.53  594.84  598.15  601.46
  604.78   611.4  618.02  621.33  624.65  628.83  634.58   641.2  647.83  654.45
  657.96  661.07  665.18  667.69  671.01  674.32  680.94  684.25  687.56  690.88
  700.81  704.55  707.46  712.49
 1645.76 1645.48  1645.3  1645.1 1644.76 1643.62 1643.35 1642.96 1641.76 1641.56
 1641.41  1641.1 1640.56 1639.26 1638.83 1638.54 1638.36  1638.3 1638.11 1637.98
 1637.69 1637.58 1637.45 1637.34 1637.17 1636.85 1636.75 1636.31 1636.23 1635.92
 1635.54 1635.49 1635.39 1635.25 1635.13 1635.13 1635.07 1634.99 1634.93 1634.91
 1634.82  1634.8 1634.77 1634.76 1634.79  1634.8 1634.83  1634.9 1634.99 1635.59
 1635.61 1635.61 1635.62  1635.8 1636.07 1636.07 1636.09 1636.44 1637.15 1637.19
 1637.22 1637.24 1637.38 1637.52 1637.56 1637.66 1637.73 1637.96 1638.12 1638.38
 1638.47 1638.63 1638.73 1638.86 1639.52 1639.66  1639.9 1640.09 1640.61 1641.18
  1642.6 1642.86 1643.38 1643.81  1644.2  1644.9 1645.48 1645.87 1646.29 1646.68
 1647.05 1647.69 1648.19 1648.47 1648.66 1648.89 1649.23 1649.58 1649.87 1650.18
 1650.25 1650.43 1650.61 1650.69 1650.76 1650.89 1651.06 1651.18  1651.2 1651.26
  1651.4 1651.41 1651.44 1651.42
                                                                                
                                                                                
                                                                                
                                                                                
                                                                                
                                                                                
                                                                                
                                                                                
                                                                                
                                                                                
                                                                                
                                
BR Coef=-1 ,-1 , 0 ,, 0 ,,,0.8,0,1.2,0,
WSPro=,,,, 1 ,,,, 0 ,,,, 0 ,,,,-1 ,-1 ,-1 , 0 , 0 , 0 , 0 , 0
Multiple Barrel Culv=2,8,11.5,60,0.013,0.4,1,8,1,1619.95,1619.35, 2,Culvert #1  , 0 ,17
  458.18  382.87  470.68  395.37
BC Culvert Barrel=1,Barrel #1,0
BC Culvert Barrel=2,Barrel #2,0
Culvert Bottom n=0.013
BC Design=,, 0 ,, 0 ,,,,,,
BC HTab HWMax=0
BC HTab TWMax=0
BC HTab MaxFlow=0
BC Use User HTab Curves=0
BC User HTab FreeFlow(D)= 0

Type RM Length L Ch R = 1 ,1756    ,117,131.8,131
BEGIN DESCRIPTION:
Merged US Survey SCB018CD
END DESCRIPTION:
XS GIS Cut Line= 4
     2028313.611      143493.184     2028256.483       143688.44
     2028270.126      143973.223       2028310.2      144232.428
#Sta/Elev= 30
       0 1644.02     109 1637.52   161.6 1640.86   168.4  1637.8   171.8 1634.09
   185.5  1632.7   198.9 1625.72   209.2  1623.9   320.1 1622.48   351.5 1623.72
   372.8 1621.58   376.9 1620.28   377.5 1619.23  401.13 1619.33     403 1620.55
   409.6 1621.64   416.1 1622.97   425.2 1629.72   429.3 1631.36   462.1 1633.14
   478.5 1635.12  492.691635.149   564.7 1637.19   581.1 1638.72  592.291641.487
   611.2 1647.18  620.791648.813  657.381649.946  691.881650.378   750.8 1650.01
#Mann= 8 ,-1 , 0
       0     .04       0   372.8    .045       0   409.6     .03       0
  492.69     .04       0  592.29     .03       0  620.79    .013       0
  657.38     .03       0  691.88    .013       0
#XS Ineff= 2 , 0
             352  1634.9     416          1634.9
Permanent Ineff=
       F       F
Bank Sta=372.8,409.6
XS Rating Curve= 0 ,0
Exp/Cntr=0.5,0.3

Type RM Length L Ch R = 1 ,1625    ,111.7,107.9,80.7
XS GIS Cut Line= 3
2028294.36950772143484.8299954152028172.19254621143831.547335092
2028265.72169299 144239.22244987
#Sta/Elev= 30
       0 1631.51    30.6 1634.93    51.5 1635.93    79.5  1633.7    97.5 1631.57
   176.8 1626.55   242.9 1624.67   277.6 1625.15   281.1 1624.55   288.1 1621.58
   300.81620.022   312.4 1618.93   319.4 1620.01   336.8 1622.78   343.7 1625.08
   347.2 1625.54   398.4 1625.66   435.4 1626.98   461.5 1625.76   492.6 1625.55
   505.3    1629   516.3 1630.09     533 1632.87     571 1633.86   610.4 1636.26
   620.9 1638.46   650.8 1648.47   657.5 1649.75   741.7 1650.75   785.9 1649.89
#Mann= 8 ,-1 , 0
       0      .1       0      30     .04       0     190      .1       0
   300.8    .045       0   319.4      .1       0     340     .03       0
  547.61     .04       0  647.61     .03       0
#Block Obstruct= 1 ,-1
413.1887456.1904 1626.98
Bank Sta=300.8,319.4
XS Rating Curve= 0 ,0
Exp/Cntr(USF)=0,0
Exp/Cntr=0.3,0.1

Type RM Length L Ch R = 1 ,1517    ,227.1,224.6,237.3
XS GIS Cut Line= 4
     2028042.321      143518.635     2028087.806      143708.371
     2028118.995      143846.125     2028230.758      144247.692
#Sta/Elev= 30
       0 1660.99    18.6 1661.71    75.9 1656.51    99.6  1652.9   120.4 1647.94
     140 1642.18  152.571641.719   160.3 1640.81   180.5 1635.37     194 1632.77
   200.8  1630.2   211.6 1623.21   227.7 1619.74   234.4  1618.2   254.3 1619.86
   261.3 1619.36  269.031620.408   281.5 1620.79   309.1  1619.8   379.6 1621.72
  418.781621.943   471.5 1622.77   480.4 1623.96     515 1631.78   574.71634.282
   583.9 1636.42  621.661648.867  635.321650.033  721.351650.633   753.1 1649.76
#Mann= 10 ,-1 , 0
       0      .1       0  152.57      .1       0   227.7    .045       0
   254.3      .1       0  269.03     .03       0  418.78     .04       0
   574.7     .03       0  621.66    .013       0  635.32     .03       0
  721.35    .013       0
#XS Ineff= 2 , 0
                          359.93         1626.48
Permanent Ineff=
       F       F
#Block Obstruct= 1 ,-1
380.9192425.6501 1626.98
Bank Sta=227.7,254.3
XS Rating Curve= 0 ,0
Exp/Cntr=0.3,0.1