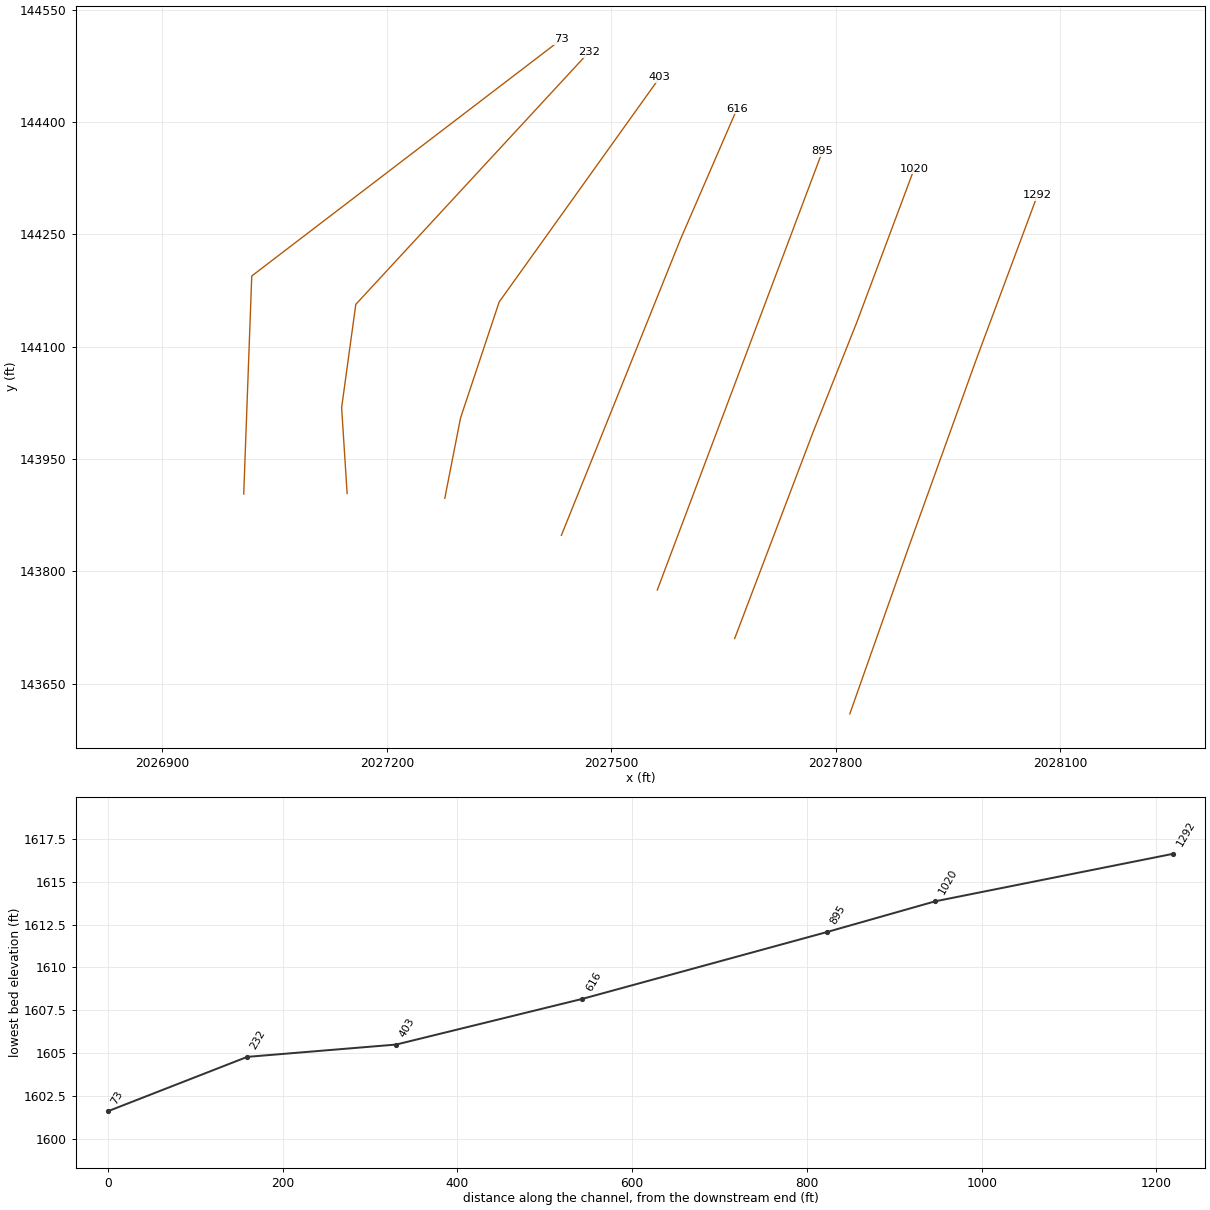
HEC-RAS study SCOTTBR.prj: SCOTTBR

--- SCOTTBR.g01 (geometry) --- (continued)

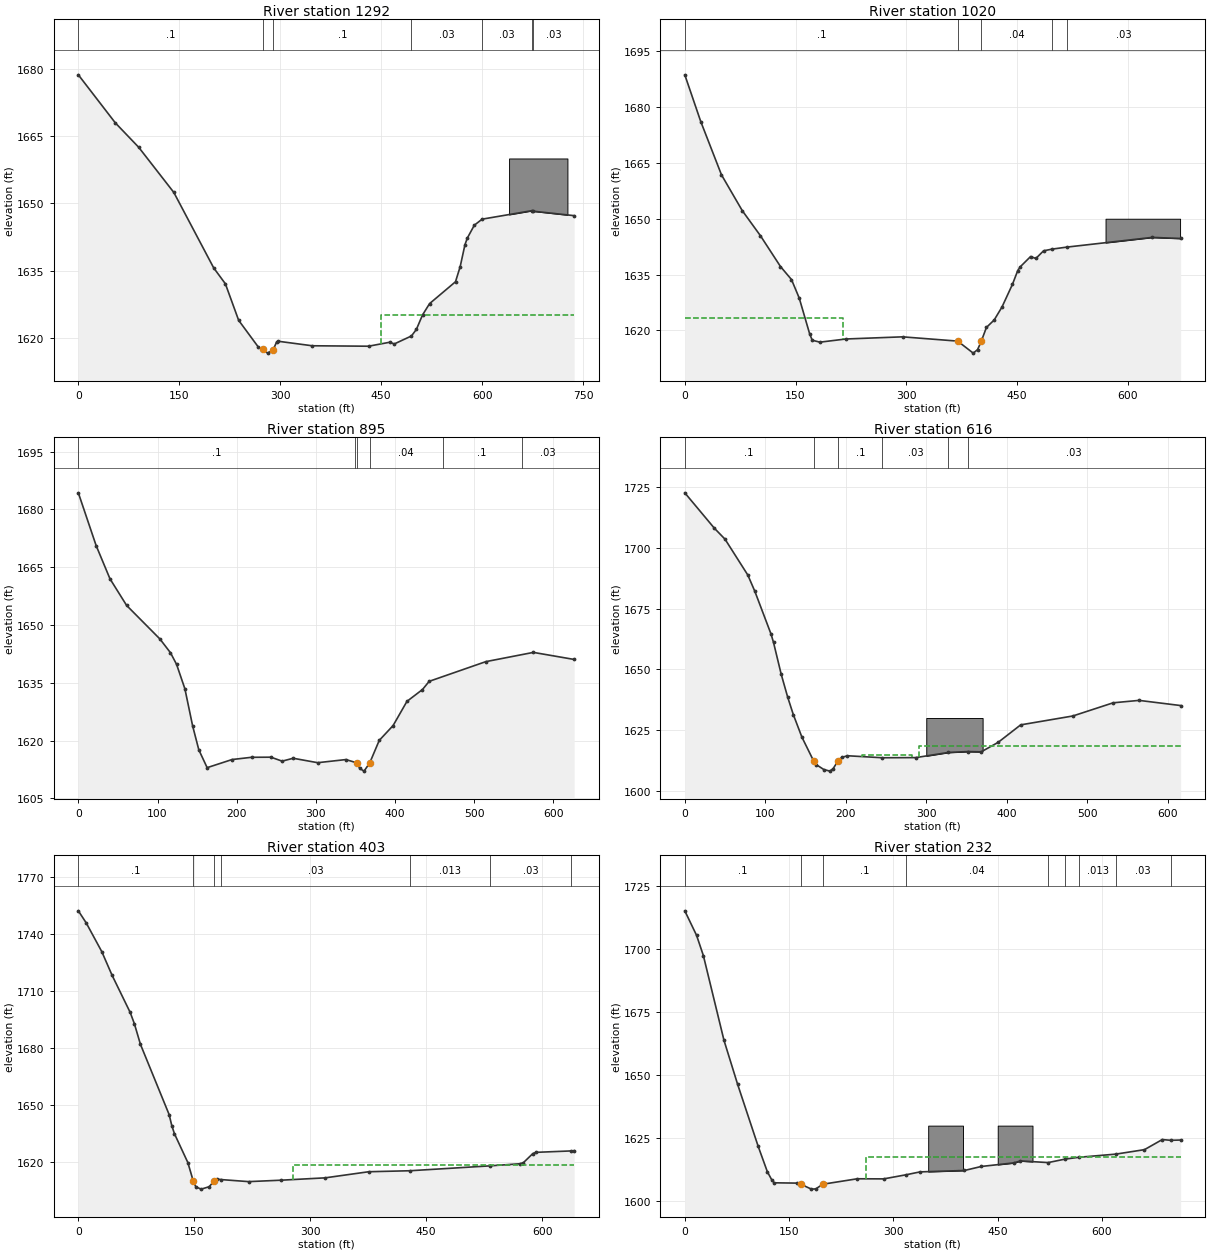
Type RM Length L Ch R = 1 ,1292    ,174.5,272.6,185.3
XS GIS Cut Line= 4
     2027818.795      143609.604      2027895.47      143826.632
     2027987.739      144082.647     2028069.612      144302.273
#Sta/Elev= 30
       0 1678.63    54.9 1667.94    89.7 1662.49   141.9 1652.43   201.1 1635.63
   218.5 1632.08   238.2 1623.95   267.3 1618.02   274.5 1617.47   281.2 1616.64
   289.5 1617.39   294.6 1619.12   297.2 1619.28   347.5 1618.28   431.2 1618.18
   462.5 1619.06   469.5 1618.69  494.971620.464   502.3 1621.93   511.4 1625.14
   521.9 1627.67   560.4 1632.54   567.4 1635.93   574.4 1640.77   577.9 1642.25
   588.4 1645.14  599.971646.481  674.27 1648.38  675.821648.256   736.7 1647.26
#Mann= 7 ,-1 , 0
       0      .1       0   274.5    .045       0   289.5      .1       0
  494.97     .03       0  599.97     .03       0  674.27     .03       0
  675.82     .03       0
#XS Ineff= 2 , 0
                          450.43         1625.14
Permanent Ineff=
       F       F
#Block Obstruct= 1 ,-1
     640   726.7    1660
Bank Sta=274.5,289.5
XS Rating Curve= 0 ,0
Exp/Cntr=0.3,0.1

Type RM Length L Ch R = 1 ,1020    ,121.3,124.2,123.8
XS GIS Cut Line= 4
     2027664.873      143710.051     2027770.138      143986.897
     2027828.033      144132.163     2027904.877      144337.429
#Sta/Elev= 30
       0 1688.69    21.6 1676.13    49.7 1661.79    77.8 1652.18   102.4 1645.44
   129.6 1637.14   144.5 1633.64     155 1628.65   169.1 1619.04   172.6 1617.33
     183 1616.81   218.2 1617.66   294.9 1618.24   369.6 1617.09   390.6 1613.86
   396.5  1614.8   401.4 1616.99   408.5 1620.77     419 1622.77   429.6 1626.27
   443.8 1632.38   450.8    1636   454.3 1637.07   468.3 1639.83   475.4 1639.31
   485.9 1641.37  497.411641.827  517.951642.381     633 1644.98   671.5 1644.69
#Mann= 5 ,-1 , 0
       0      .1       0   369.6    .045       0   401.4     .04       0
  497.41      .1       0  517.95     .03       0
#XS Ineff= 2 , 0
          214.61 1623.42
Permanent Ineff=
       F       F
#Block Obstruct= 1 ,-1
569.7969 670.761    1650
Bank Sta=369.6,401.4
XS Rating Curve= 0 ,0
Exp/Cntr=0.3,0.1

Type RM Length L Ch R = 1 ,895     ,146.6,279.5,221.5
XS GIS Cut Line= 2
2027561.46291431143774.8891195172027782.28981949144360.975662456
#Sta/Elev= 30
       0  1684.3    22.5  1670.6      40 1661.97      61 1655.07   103.1 1646.35
   116.4 1642.79   124.1 1639.77   134.6 1633.43   144.4 1623.78   152.2 1617.58
   162.7 1612.96   194.2 1615.07   218.8 1615.65   243.3 1615.68   257.4 1614.65
   271.4  1615.4   302.3 1614.25     338 1615.06     352 1614.19   355.5 1612.75
   360.9 1612.06  368.09  1614.2   380.1 1620.04   397.6 1623.89   415.1 1630.17
   434.7 1633.24   443.2 1635.37   514.7 1640.48   574.8 1642.88   626.3 1641.05
#Mann= 6 ,-1 , 0
       0      .1       0     350     .04       0     352    .045       0
  368.09     .04       0     460      .1       0     560     .03       0
Bank Sta=352,368.09
XS Rating Curve= 0 ,0
Exp/Cntr(USF)=0,0
Exp/Cntr=0.3,0.1

Type RM Length L Ch R = 1 ,616     ,190.3,213.1,196.5
XS GIS Cut Line= 4
      2027433.29      143847.948     2027479.607      143962.686
      2027592.24      144242.691     2027668.031      144417.431
#Sta/Elev= 30
       0 1722.57    36.6 1708.07      50  1703.5    78.3 1688.77      87  1682.1
   107.2 1664.45   110.2 1661.09   119.8 1647.95   127.8  1638.6   134.8 1631.42
   145.5 1622.13   160.1 1612.31   163.2 1610.85   172.7 1608.82   180.3 1608.16
   184.4 1609.23   190.4  1612.4     195 1613.81   202.1 1614.48  245.591613.657
     287 1613.72  327.581615.843  351.68  1616.2   368.3  1616.1   389.4 1620.01
   417.3 1627.18   482.1 1630.83   532.2 1636.25   564.4 1637.24     616 1635.12
#Mann= 6 ,-1 , 0
       0      .1       0   160.1    .045       0   190.4      .1       0
  245.59     .03       0  327.58     .04       0  351.68     .03       0
#XS Ineff= 2 ,-1
  220.49  282.09 1614.72  291.22  642.461618.477
Permanent Ineff=
       F       F
#Block Obstruct= 1 ,-1
     300     370    1630
Bank Sta=160.1,190.4
XS Rating Curve= 0 ,0
Exp/Cntr=0.3,0.1

Type RM Length L Ch R = 1 ,403     ,169.3,170.4,184.2
XS GIS Cut Line= 4
     2027277.498      143897.422     2027298.551      144004.792
     2027350.131      144159.532     2027564.871      144459.537
#Sta/Elev= 30
       0 1752.05    10.2 1745.69    30.3 1730.59    43.6 1718.16    67.1 1698.53
    72.5 1692.61    80.4  1681.7   117.5 1644.73   120.9 1638.95   124.4 1634.63
   141.7 1619.47   148.8  1609.6   152.1 1606.64     159 1605.49   169.3 1606.76
   175.3  1609.6   179.7 1610.79   184.21610.533   220.4 1609.44   262.7  1610.2
   319.3 1611.43   375.7 1614.65  429.071615.171   532.5 1617.74   571.8 1618.87
   575.8 1619.42   587.9 1624.16   591.9 1624.86  638.051625.617   641.5 1625.73
#Mann= 7 ,-1 , 0
       0      .1       0   148.8    .045       0   175.3      .1       0
   184.2     .03       0  429.07    .013       0   532.5     .03       0
  638.05    .013       0
#XS Ineff= 2 , 0
                          277.79         1618.37
Permanent Ineff=
       F       F
Bank Sta=148.8,175.3
XS Rating Curve= 0 ,0
Exp/Cntr=0.3,0.1

Type RM Length L Ch R = 1 ,232     ,141.2,159.6,160.2
Node Name=A
XS GIS Cut Line= 4
      2027146.97      143903.738     2027139.601      144018.477
     2027158.549      144156.374     2027470.133      144493.221
#Sta/Elev= 30
       0 1715.33    16.9 1705.61    26.7 1697.56    56.3 1663.93      76 1646.37
   105.6 1621.71   118.8 1611.61   125.4 1608.29   128.7 1607.28   161.9 1607.16
   167.5 1606.62   182.1 1604.77   188.4 1604.86   198.3 1606.71     248 1608.88
     286 1608.84  318.021610.461   338.3 1611.62   402.2 1612.18   426.5 1613.78
     473 1615.19   482.7 1615.97  522.511615.317  546.561616.683  567.241617.435
  619.871618.681     661 1620.45   686.6 1624.46   698.71624.169     713 1624.27
#Mann= 9 ,-1 , 0
       0      .1       0   167.5    .045       0   198.3      .1       0
  318.02     .04       0  522.51     .04       0  546.56     .03       0
  567.24    .013       0  619.87     .03       0   698.7    .013       0
#XS Ineff= 2 , 0
                          260.47         1617.52
Permanent Ineff=
       F       F
#Block Obstruct= 2 ,-1
349.9873399.9855    1630449.9836499.9818    1630
Bank Sta=167.5,198.3
XS Rating Curve= 0 ,0
Exp/Cntr=0.3,0.1

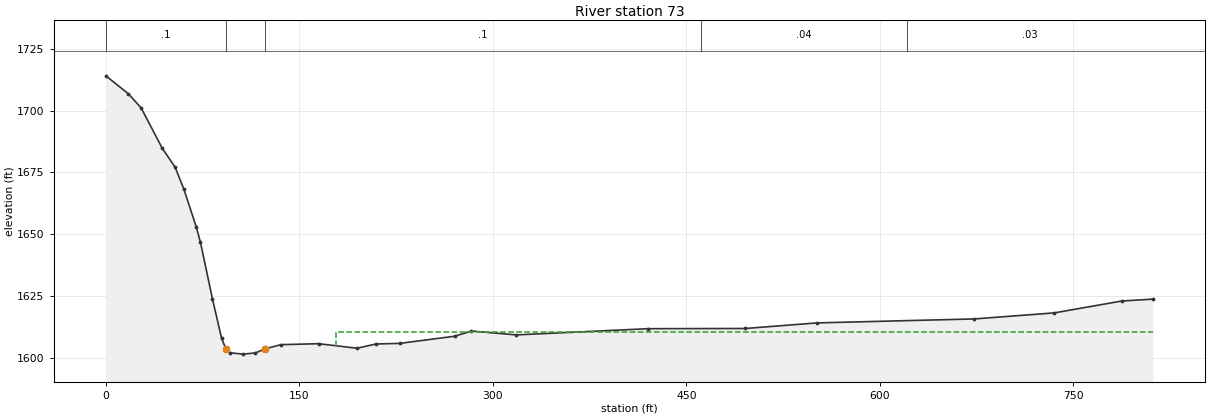
Type RM Length L Ch R = 1 ,73      ,,,
XS GIS Cut Line= 3
2027008.75093143143903.1269948572027019.49386196144194.260412011
2027433.09668706144510.102569367
#Sta/Elev= 30
       0 1714.05    17.5 1706.75    27.3 1701.09    43.7 1684.78    53.6 1677.16
    60.5  1668.2      70 1653.02    73.3 1646.78    82.6 1623.89    89.7 1607.95
      93 1603.76    96.2 1602.15   106.1 1601.59   115.9 1602.07  123.68 1603.76
   135.6 1605.41   164.9  1605.8   194.7 1603.97   209.3 1605.69   227.6 1605.92
   270.3 1608.82   283.4 1610.92   318.2 1609.36   420.3 1611.87   495.7 1611.95
   551.3 1614.21   673.1 1615.81   735.1 1618.25   787.7 1623.07811.7386 1623.82
#Mann= 5 ,-1 , 0
       0      .1       0      93    .045       0  123.68      .1       0
  461.33     .04       0  621.33     .03       0
#XS Ineff= 2 , 0
                          178.57         1610.59
Permanent Ineff=
       F       F
Bank Sta=93,123.68
XS Rating Curve= 0 ,0
Exp/Cntr(USF)=0,0
Exp/Cntr=0.3,0.1
LCMann Table=0

Chan Stop Cuts=-1
Use User Specified Reach Order=0
Composite Channel Slope=5